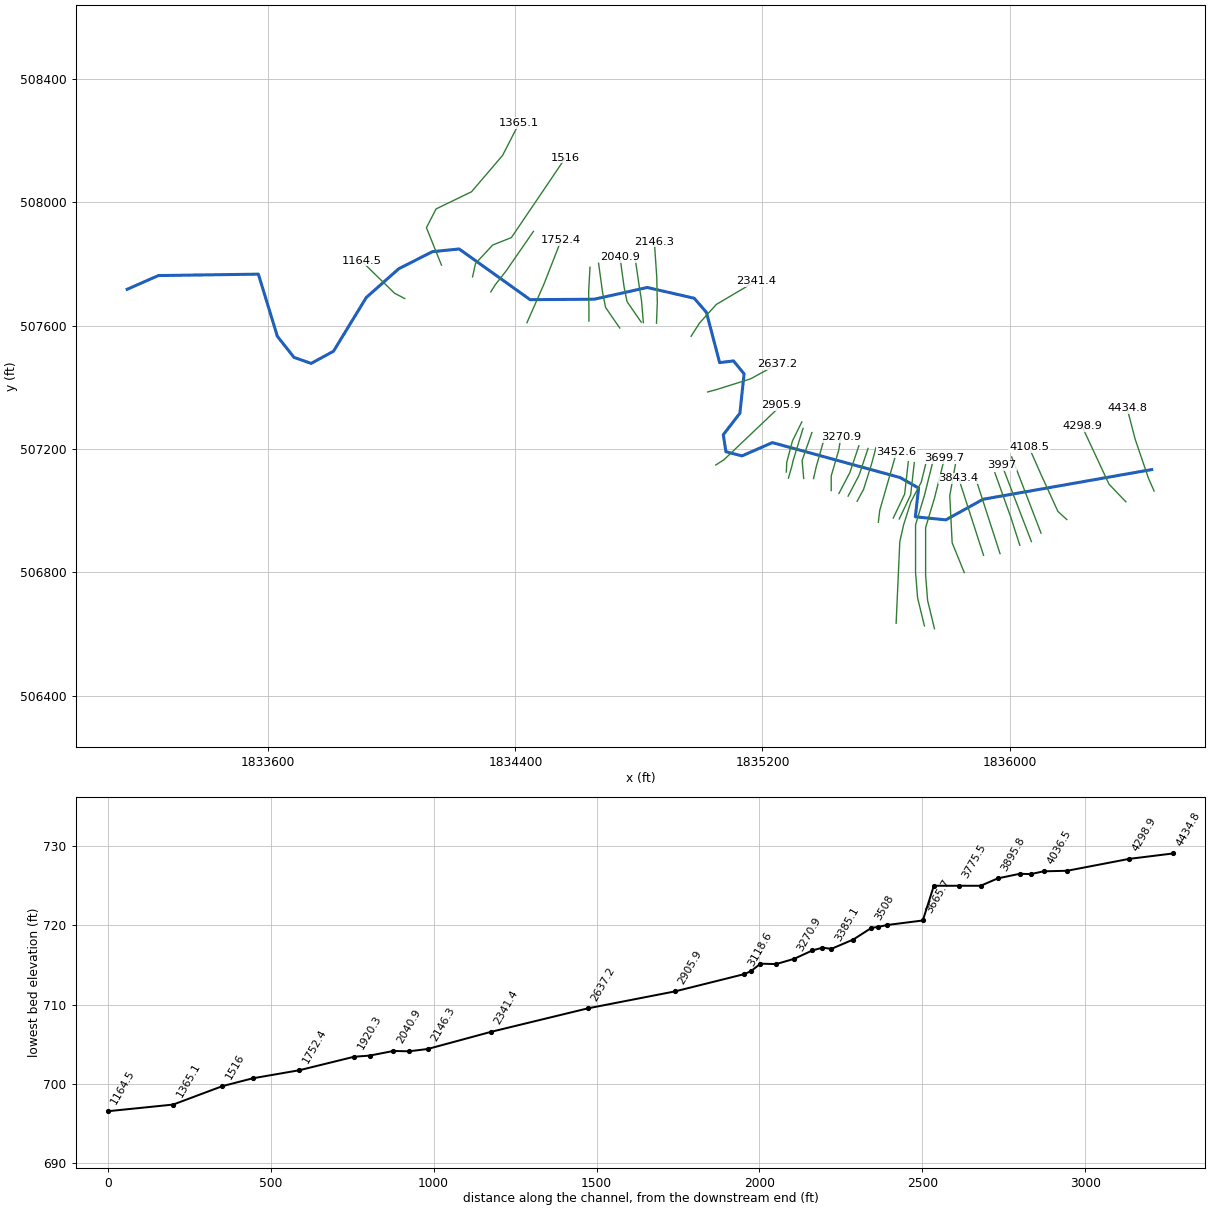
--- INDIANSCK.prj (project) ---

Proj Title=INDIANSCK
Current Plan=p01
Default Exp/Contr=0,0
English Units
Geom File=g01
Flow File=f01
Plan File=p01
BEGIN DESCRIPTION:
END DESCRIPTION:
DSS Export Rating Curves= 0
DSS Export Rating Curve Sorted= 0
DSS Export Volume Flow Curves= 0
DXF OffsetX= 0
DXF OffsetY= 0
DXF ScaleX= 0
DXF ScaleY= 0

--- INDIANSCK.p01 (plan) ---

Plan Title=Floodplain
Program Version=4.00
Geom File=g01
Flow File=f01
K Sum by GR=0
Std Step Tol=0.01
Critical Tol=0.01
Num of Std Step Trials=20
Max Error Tol=0.3
Flow Tol Ratio=0.001
Split Flow NTrial=30
Split Flow Tol=0.02
Split Flow Ratio=0.02
Log Output Level=0
Friction Slope Method=1
Unsteady Friction Slope Method=2
Unsteady Bridges Friction Slope Method=1
Global Log Level=0
CheckData=False
Run HTab=0
Run UNet=0
Run PostProcess=0
UNET Theta=0
UNET Theta Warmup=0
UNET ZTol=0
UNET ZSATol=0
UNET MxIter=0
UNET MaxInSteps=0
UNET DtIC=0
UNET DtMin=0
UNET MaxCRTS=0
UNET WFStab=0
UNET SFStab=0
UNET WFX=0
UNET SFX=0
UNET DSS MLevel=0
UNET DZMax Abort=0
UNET Convert EG Bridges=0
UNET Use Existing IB Tables=0
UNET Froude Limit=0
UNET Froude Power=0
Write IC File=0
Echo Input=False
Echo Output=False
Write Detailed=0

--- INDIANSCK.f01 (steady flow) ---

Flow Title=NFF Regression Equation
Program Version=4.10
Number of Profiles= 1
Profile Names=P100yr
River Rch & RM=INDIANSCK,Main            ,4434.8
 879.031
River Rch & RM=INDIANSCK,Main            ,3452.6
1216.879
River Rch & RM=INDIANSCK,Main            ,1164.5
1409.821
River Rch & RM=INDIANSCK,Main            ,446
1415.476
Boundary for River Rch & Prof#=INDIANSCK,Main            , 1
Up Type= 0
Dn Type= 1
Dn Known WS=693.7
DSS Import GetInterval= 0
DSS Import GetPeak= 0
DSS Import FillOption= 0

--- INDIANSCK.g01 (geometry) ---

Geom Title=USGS 10m DEM
Program Version=4.10

River Reach=INDIANSCK       ,Main
Reach XY= 30
     1836460.001      507133.458     1835914.226      507037.199
     1835793.706      506970.397     1835694.811      506980.286
     1835705.408      507073.529     1835646.071      507107.436
     1835231.995      507221.003     1835133.621      507177.866
     1835081.538      507191.408     1835073.204      507246.616
      1835126.85      507316.408     1835140.434      507444.007
     1835106.205       507485.97     1835061.225       507480.47
     1835018.517      507643.491     1834978.934      507689.324
      1834826.85       507724.22     1834655.496      507686.199
     1834447.684      507684.637     1834217.996       507849.22
     1834131.538      507840.366     1834022.684      507785.158
     1833917.475      507691.929     1833811.225      507517.449
     1833738.829      507477.866       1833683.1      507497.658
     1833629.454      507565.887     1833567.996      507767.449
     1833244.385      507762.903     1833143.148      507718.334

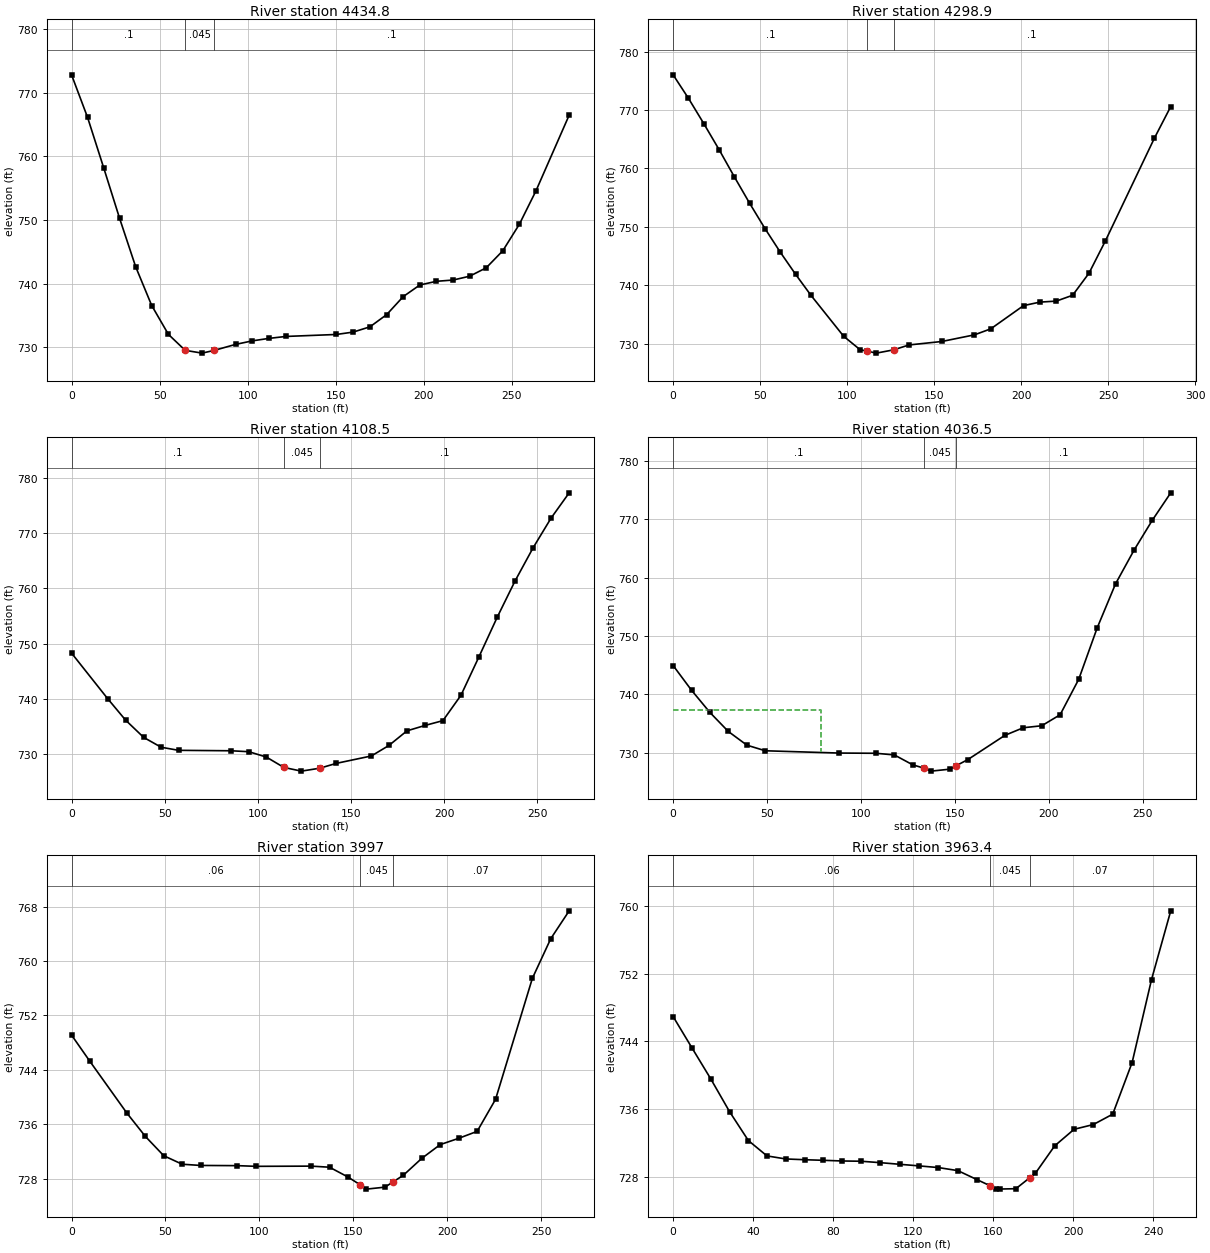
Type RM Length L Ch R = 1 ,4434.8  ,133.5,135.9,138.3
XS GIS Cut Line= 4
     1836467.692       507063.96     1836449.463      507105.626
     1836406.494      507231.929     1836380.453      507332.189
#Sta/Elev= 28
       0  772.79     9.1   766.1    18.2  758.23    27.3  750.23    36.4  742.65
    45.5  736.56      55  732.02    64.5  729.52    74.1  729.08      81  729.51
    93.1  730.45   102.7  731.01   112.2   731.4   121.7   731.7   150.3  732.01
   159.8  732.38   169.4  733.21   178.9  735.13   188.3  737.96   197.7  739.78
   207.1  740.36   216.6  740.56     226  741.16   235.4  742.48   244.8  745.15
   254.2  749.31   263.6  754.54   282.5  766.46
#Mann= 3 , 0 , 0
       0      .1       0    64.5    .045       0      81      .1       0
Bank Sta=64.5,81
XS Rating Curve= 0 ,0
Exp/Cntr=0.3,0.1

Type RM Length L Ch R = 1 ,4298.9  ,190.5,190.4,190
XS GIS Cut Line= 3
     1836376.546      507028.804     1836321.859      507086.095
     1836234.619      507273.595
#Sta/Elev= 27
       0  776.01     8.8     772    17.6  767.68    26.4  763.22    35.2  758.55
      44  754.02    52.8   749.7    61.6  745.66    70.4  741.87    79.2  738.29
      98  731.28   107.4  728.99   111.7  728.72   116.8  728.39   126.7  728.95
   135.6  729.79   154.4  730.38   173.2  731.52   182.6  732.55   201.4  736.52
   210.8  737.12   220.2  737.29   229.6  738.29     239  742.06   248.4  747.57
   276.6  765.17     286  770.58
#Mann= 3 , 0 , 0
       0      .1       0   111.7    .045       0   126.7      .1       0
Bank Sta=111.7,126.7
XS Rating Curve= 0 ,0
Exp/Cntr=0.3,0.1

Type RM Length L Ch R = 1 ,4108.5  ,73.1,72.1,70.4
XS GIS Cut Line= 4
      1836185.14      506971.512     1836156.494      506997.554
     1836101.807      507117.345     1836062.744      507205.887
#Sta/Elev= 25
       0  748.28    19.4  740.02      29  736.14    38.7  733.01    48.1  731.22
    57.5  730.66    85.7  730.58    95.2  730.41   104.6  729.44     114  727.56
   123.4  726.89   133.3  727.42   142.2   728.3     161  729.64   170.4  731.54
   180.1  734.19   189.8  735.17   199.4  736.04   209.1  740.64   218.8  747.64
   228.5  754.74   238.1  761.33   247.8  767.35   257.5  772.76   267.2  777.33
#Mann= 3 , 0 , 0
       0      .1       0     114    .045       0   133.3      .1       0
Bank Sta=114,133.3
XS Rating Curve= 0 ,0
Exp/Cntr=0.3,0.1

Type RM Length L Ch R = 1 ,4036.5  ,39.6,39.5,39.6
XS GIS Cut Line= 2
     1836101.807      506927.241     1836006.755      507174.637
#Sta/Elev= 25
       0  744.93     9.8  740.69    19.6  736.88    29.4  733.62    39.3  731.27
    49.1  730.31    88.3  729.92     108  729.88   117.8   729.6   127.6   727.9
  133.39  727.35   137.4  726.82   147.2  727.15   150.7  727.74     157  728.81
   176.7  732.96   186.5  734.26   196.3   734.6   206.1  736.49     216  742.57
   225.8  751.36   235.6  758.93   245.4  764.68   255.2  769.85     265  774.54
#Mann= 3 , 0 , 0
       0      .1       0  133.39    .045       0   150.7      .1       0
#XS Ineff= 2 , 0
           78.69  737.25
Permanent Ineff=
       F       F
Bank Sta=133.39,150.7
XS Rating Curve= 0 ,0
Exp/Cntr=0.3,0.1

Type RM Length L Ch R = 1 ,3997    ,33.7,33.6,32.7
XS GIS Cut Line= 2
     1836070.557      506899.897     1835975.505      507147.293
#Sta/Elev= 25
       0  749.11     9.8  745.24    29.4  737.67    39.3  734.22    49.1  731.38
    58.9  730.13    68.7  729.95    88.3  729.92    98.2  729.82   127.6  729.85
   137.4  729.69   147.2  728.25  153.85  727.08     157  726.47   166.9  726.76
   171.1  727.51   176.7  728.51   186.5  730.99   196.3  733.01   206.1  733.93
     216  734.96   225.8  739.67   245.4  757.45   255.2  763.28     265  767.37
#Mann= 3 , 0 , 0
       0     .06       0  153.85    .045       0   171.1     .07       0
Bank Sta=153.85,171.1
XS Rating Curve= 0 ,0
Exp/Cntr=0.3,0.1

Type RM Length L Ch R = 1 ,3963.4  ,68.6,67.6,67.1
XS GIS Cut Line= 3
     1836032.981      506888.111     1836004.335      506977.521
     1835952.252      507123.354
#Sta/Elev= 30
       0  746.93     9.4  743.23    18.8  739.56    28.2  735.68    37.6  732.26
    46.9  730.44    56.3  730.08    65.7  729.99    75.1  729.92    84.5  729.84
    93.9  729.81   103.6  729.64   113.2  729.45   122.9  729.26   132.6  729.06
   142.3   728.7     152  727.62  158.33  726.92   161.6  726.51   163.2  726.52
   171.3  726.56   178.2  727.85     181  728.37   190.7  731.63   200.4  733.59
     210  734.15   219.7  735.38   229.4  741.49   239.1  751.31   248.7  759.44
#Mann= 3 , 0 , 0
       0     .06       0  158.33    .045       0   178.2     .07       0
Bank Sta=158.33,178.2
XS Rating Curve= 0 ,0
Exp/Cntr=0.3,0.1

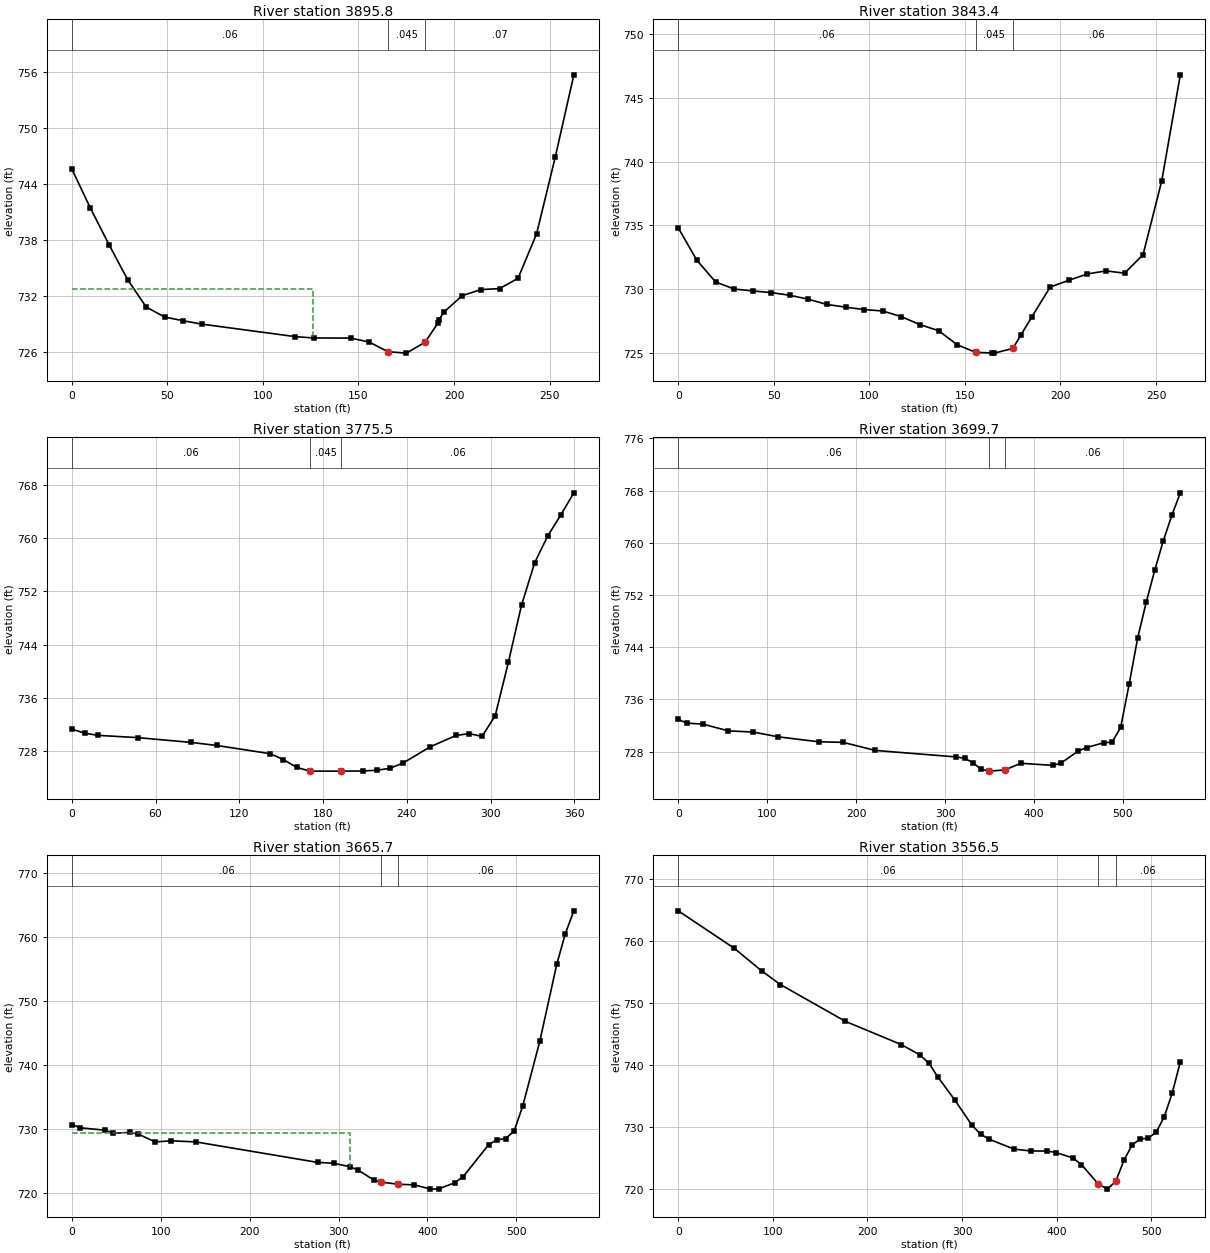
Type RM Length L Ch R = 1 ,3895.8  ,52.5,52.4,52.4
XS GIS Cut Line= 2
     1835968.994      506860.835     1835888.265      507110.835
#Sta/Elev= 25
       0  745.64     9.7  741.46    19.5  737.53    29.2   733.8    38.9  730.87
    48.6  729.79    58.4  729.39    68.1  729.03   116.8   727.7   126.5  727.55
     146  727.54   155.7  727.11   165.4  726.08   175.1  725.93   184.9   727.1
  191.59  729.15   192.1  729.48   194.6   730.3   204.3  732.08   214.1  732.73
   223.8  732.83   233.5  733.93   243.2  738.69     253  746.92   262.7   755.7
#Mann= 3 , 0 , 0
       0     .06       0   165.4    .045       0   184.9     .07       0
#XS Ineff= 2 , 0
          126.17  732.79
Permanent Ineff=
       F       F
Bank Sta=165.4,184.9
XS Rating Curve= 0 ,0
Exp/Cntr=0.3,0.1

Type RM Length L Ch R = 1 ,3843.4  ,74.1,67.9,58.9
XS GIS Cut Line= 2
     1835915.609      506855.626      1835834.88      507105.626
#Sta/Elev= 30
       0  734.81     9.7  732.28    19.5  730.58    29.2  730.02    38.9  729.87
    48.6  729.74    58.4  729.53    68.1  729.22    77.8  728.81    87.6   728.6
    97.3  728.41     107   728.3   116.8  727.85   126.5  727.23   136.2  726.76
     146  725.65   155.7  725.06   164.4  725.01   165.4     725   175.1  725.37
   179.4  726.44   184.9  727.81   194.6  730.17   204.3   730.7   214.1   731.2
   223.8  731.44   233.5  731.26   243.2   732.7     253   738.5   262.7  746.79
#Mann= 3 , 0 , 0
       0     .06       0   155.7    .045       0   175.1     .06       0
Bank Sta=155.7,175.1
XS Rating Curve= 0 ,0
Exp/Cntr=0.3,0.1

Type RM Length L Ch R = 1 ,3775.5  ,83.3,75.8,70.9
XS GIS Cut Line= 4
     1835853.109      506799.637     1835814.046      506895.991
     1835806.234      507048.335     1835824.463      507149.897
#Sta/Elev= 26
       0  731.31     9.4  730.69    18.9  730.37    47.3  730.03    85.1  729.32
     104  728.85   142.1  727.62   151.6  726.74   161.2  725.55   170.7     725
   192.9     725   208.8  725.02   218.4  725.13   227.9  725.42   237.4  726.22
   256.5  728.62   275.3  730.36   284.7  730.63     294  730.22   303.4  733.35
   312.8  741.35   322.2  749.91   331.6  756.27   340.9  760.28   350.3  763.45
   359.7  766.79
#Mann= 3 , 0 , 0
       0     .06       0   170.7    .045       0   192.9     .06       0
Bank Sta=170.7,192.9
XS Rating Curve= 0 ,0
Exp/Cntr=0.3,0.1

Type RM Length L Ch R = 1 ,3699.7  ,34,34,101.6
XS GIS Cut Line= 6
     1835756.755      506617.345     1835734.619      506708.491
     1835728.109      506790.522     1835728.109       506945.47
     1835756.755      507040.522     1835789.307      507170.731
#Sta/Elev= 30
       0  732.92     9.4  732.37    28.1  732.19    56.3  731.17    84.4  730.99
   112.1  730.26   157.8   729.5   185.2  729.41   221.7  728.17   312.9  727.17
     322  726.96   331.1  726.32   340.2  725.33   349.2     725   367.2  725.18
   385.3   726.2   421.4  725.88   430.4  726.22   449.6  728.07   459.2  728.61
   478.3  729.34   487.9  729.45   497.5  731.69   507.1  738.36   516.7  745.43
   526.3   750.9   535.9  755.81   545.4  760.27     555  764.18   564.6  767.65
#Mann= 3 , 0 , 0
       0     .06       0   349.2    .045       0   367.2     .06       0
Bank Sta=349.2,367.2
XS Rating Curve= 0 ,0
Exp/Cntr=0.3,0.1

Type RM Length L Ch R = 1 ,3665.7  ,103.5,109.2,34.2
XS GIS Cut Line= 6
     1835724.203       506626.46     1835702.067      506717.606
     1835695.557      506799.637     1835695.557      506954.585
     1835724.203      507049.637     1835756.755      507179.845
#Sta/Elev= 30
       0  730.72     9.4  730.21    37.5  729.83    46.9  729.36    65.7  729.48
      75   729.2    93.8     728   112.1  728.17   139.5     728   276.4   724.8
   294.6  724.66   312.9  724.12     322   723.6   340.2     722     348  721.72
   367.2  721.38   385.3  721.29   403.3  720.62   412.4  720.64   430.4  721.61
     440  722.54   468.8  727.57   478.3  728.34   487.9   728.5   497.5  729.73
   507.1   733.6   526.3  743.72   545.4  755.77     555  760.54   564.6  764.12
#Mann= 3 , 0 , 0
       0     .06       0     348    .045       0   367.2     .06       0
#XS Ineff= 2 , 0
          312.72  729.38
Permanent Ineff=
       F       F
Bank Sta=348,367.2
XS Rating Curve= 0 ,0
Exp/Cntr=0.3,0.1

Type RM Length L Ch R = 1 ,3556.5  ,29.4,28.2,32.8
XS GIS Cut Line= 6
     1835632.623      506634.923     1835644.559       506899.68
     1835656.494      506952.849     1835680.366      507028.804
     1835714.003      507092.823     1835728.109      507150.331
#Sta/Elev= 30
       0  764.89    58.9  758.89    88.3   755.2     108  753.01   176.7  747.08
   235.6  743.35   255.2   741.7     265  740.35   274.1  738.18   292.3  734.42
   310.4  730.35   319.5  728.92   328.4  728.11   354.9   726.5   372.6   726.2
   390.3  726.18   399.1  725.95   417.2  725.07   426.2     724   443.8  720.92
   453.4  720.05   462.4  721.29   471.4   724.8   479.9  727.18   488.4  728.13
   496.8  728.25   505.3  729.25   513.8  731.73   522.2  735.56   530.7  740.55
#Mann= 3 , 0 , 0
       0     .06       0   443.8    .045       0   462.4     .06       0
Bank Sta=443.8,462.4
XS Rating Curve= 0 ,0
Exp/Cntr=0.3,0.1

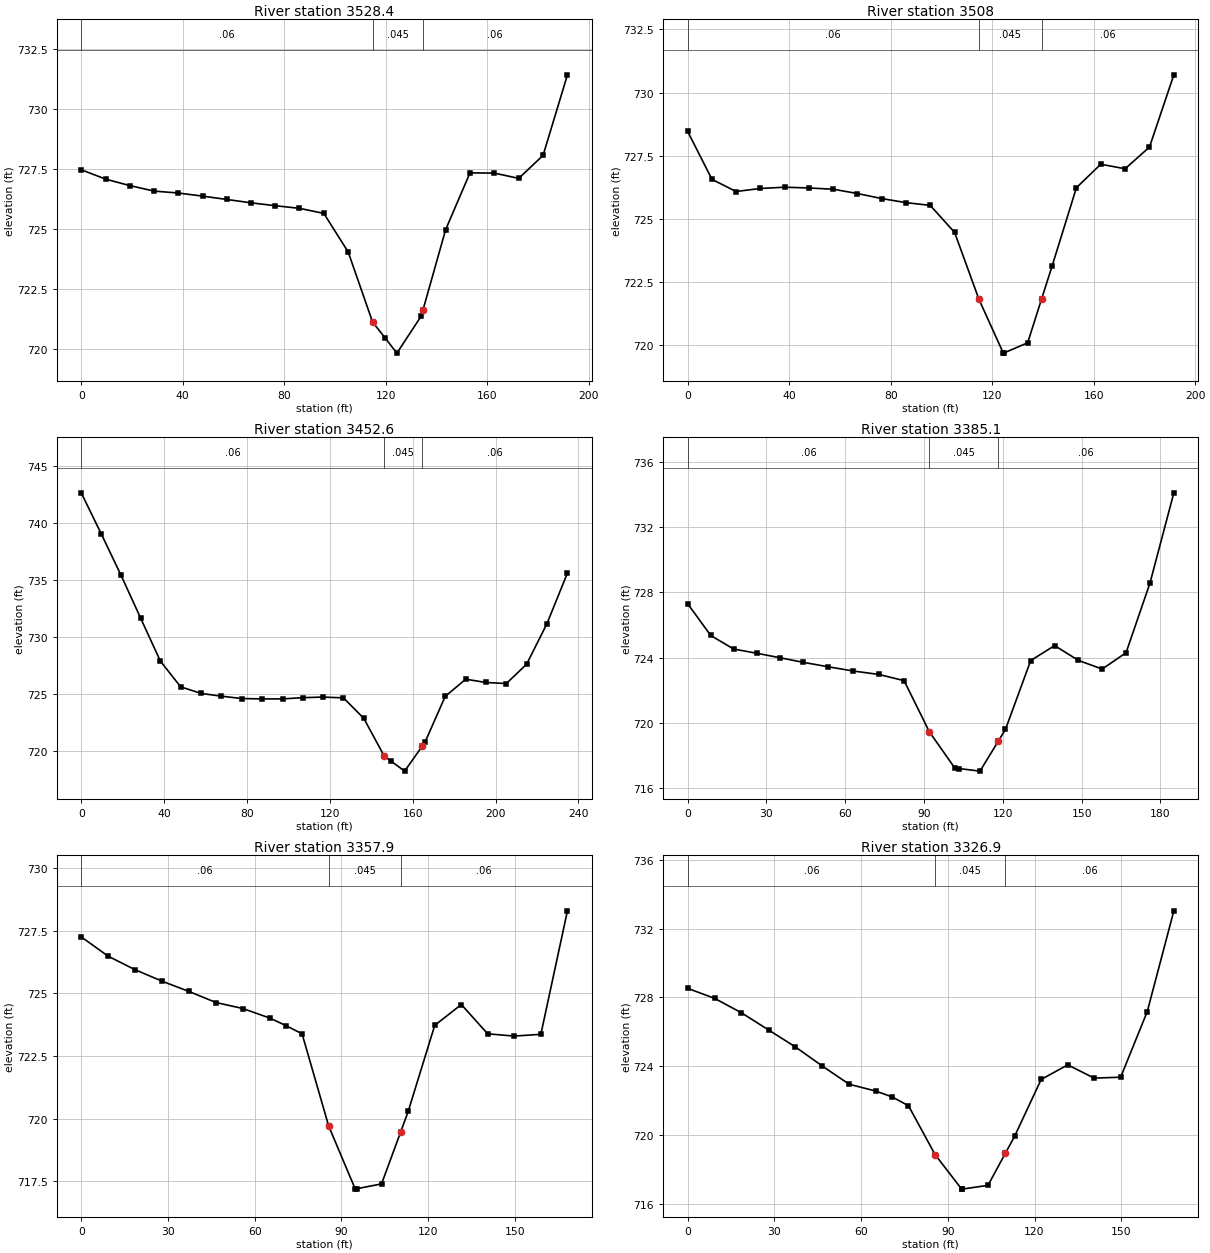
Type RM Length L Ch R = 1 ,3528.4  ,20.9,20.4,20.4
XS GIS Cut Line= 3
     1835642.866      506973.508     1835679.671      507051.286
     1835691.477      507156.147
#Sta/Elev= 23
       0  727.46     9.6  727.07    19.1   726.8    28.7  726.57    38.2  726.49
    47.8  726.36    57.4  726.22    66.9  726.08    76.5  725.96      86  725.85
    95.6  725.64   105.2  724.03   114.8  721.11   119.7  720.45   124.4  719.81
     134  721.36   134.7  721.62   143.6  724.96   153.2  727.33   162.8  727.32
   172.4   727.1     182  728.06   191.6  731.42
#Mann= 3 , 0 , 0
       0     .06       0   114.8    .045       0   134.7     .06       0
Bank Sta=114.8,134.7
XS Rating Curve= 0 ,0
Exp/Cntr=0.3,0.1

Type RM Length L Ch R = 1 ,3508    ,59.3,55.4,51.4
XS GIS Cut Line= 3
     1835623.421      506976.286     1835660.227      507054.064
     1835672.033      507158.925
#Sta/Elev= 23
       0  728.46     9.6  726.56    19.1  726.08    28.7   726.2    38.2  726.25
    47.8  726.22    57.4  726.17    66.9     726    76.5   725.8      86  725.64
    95.6  725.53   105.2  724.46   114.8  721.81   124.4  719.68   124.5  719.68
     134  720.09   139.5  721.83   143.6  723.12   153.2  726.23   162.8  727.16
   172.4  726.98     182  727.84   191.6   730.7
#Mann= 3 , 0 , 0
       0     .06       0   114.8    .045       0   139.5     .06       0
Bank Sta=114.8,139.5
XS Rating Curve= 0 ,0
Exp/Cntr=0.3,0.1

Type RM Length L Ch R = 1 ,3452.6  ,68.1,67.5,67.1
XS GIS Cut Line= 3
     1835575.114      506962.614     1835579.454      507000.592
     1835633.708      507189.394
#Sta/Elev= 27
       0  742.65     9.6  739.07    19.1  735.46    28.7  731.64    38.2  727.88
      48  725.62    57.9  725.04    67.7   724.8    77.5  724.59    87.3  724.56
    97.2  724.56     107  724.67   116.8  724.72   126.6  724.65   136.4  722.85
   146.3  719.53   149.7  719.08   156.1  718.22   164.7  720.43   165.9  720.74
   175.7  724.78   185.6  726.29   195.4     726   205.2  725.91     215  727.61
   224.8  731.16   234.7  735.61
#Mann= 3 , 0 , 0
       0     .06       0   146.3    .045       0   164.7     .06       0
Bank Sta=146.3,164.7
XS Rating Curve= 0 ,0
Exp/Cntr=0.3,0.1

Type RM Length L Ch R = 1 ,3385.1  ,27.6,27.2,26.7
XS GIS Cut Line= 4
     1835506.353      507030.637     1835527.187      507069.179
     1835553.228      507151.991     1835567.291      507204.596
#Sta/Elev= 23
       0  727.31     8.8  725.36    17.5  724.53    26.3  724.27      35     724
    43.8  723.72    53.5  723.44    63.1  723.18    72.8  722.97    82.4  722.59
      92  719.46   101.7  717.23   103.2   717.2   111.3  717.04   118.2  718.86
     121   719.6   130.6  723.82   139.7  724.74   148.8  723.83   157.8   723.3
   166.9   724.3     176  728.57   185.1  734.11
#Mann= 3 , 0 , 0
       0     .06       0      92    .045       0   118.2     .06       0
Bank Sta=92,118.2
XS Rating Curve= 0 ,0
Exp/Cntr=0.3,0.1

Type RM Length L Ch R = 1 ,3357.9  ,31,31,31
XS GIS Cut Line= 4
     1835477.187      507047.304     1835507.395      507105.116
     1835512.603      507115.012      1835541.77      507201.991
#Sta/Elev= 22
       0  727.26     9.3  726.49    18.6  725.95      28  725.49    37.3  725.08
    46.6  724.64    55.9   724.4    65.2  724.02    70.8  723.72    76.4  723.39
    85.6  719.71    94.8  717.19    95.5  717.21   103.9   717.4   110.5  719.47
   113.1  720.29   122.3  723.73   131.5  724.56   140.6  723.39   149.8   723.3
     159  723.37   168.2   728.3
#Mann= 3 , 0 , 0
       0     .06       0    85.6    .045       0   110.5     .06       0
Bank Sta=85.6,110.5
XS Rating Curve= 0 ,0
Exp/Cntr=0.3,0.1

Type RM Length L Ch R = 1 ,3326.9  ,55.1,56.1,56.9
XS GIS Cut Line= 4
     1835447.499      507056.158     1835477.707      507113.971
     1835482.916      507123.866     1835512.082      507210.846
#Sta/Elev= 22
       0  728.52     9.3  727.94    18.6   727.1      28   726.1    37.3  725.11
    46.6     724    55.9  722.94    65.2  722.54    70.8   722.2    76.4  721.69
    85.6  718.85    94.8  716.84    94.9  716.84   103.9  717.06   109.9  718.92
   113.1  719.91   122.3  723.22   131.5  724.07   140.6   723.3   149.8  723.35
     159  727.17   168.2  733.03
#Mann= 3 , 0 , 0
       0     .06       0    85.6    .045       0   109.9     .06       0
Bank Sta=85.6,109.9
XS Rating Curve= 0 ,0
Exp/Cntr=0.3,0.1

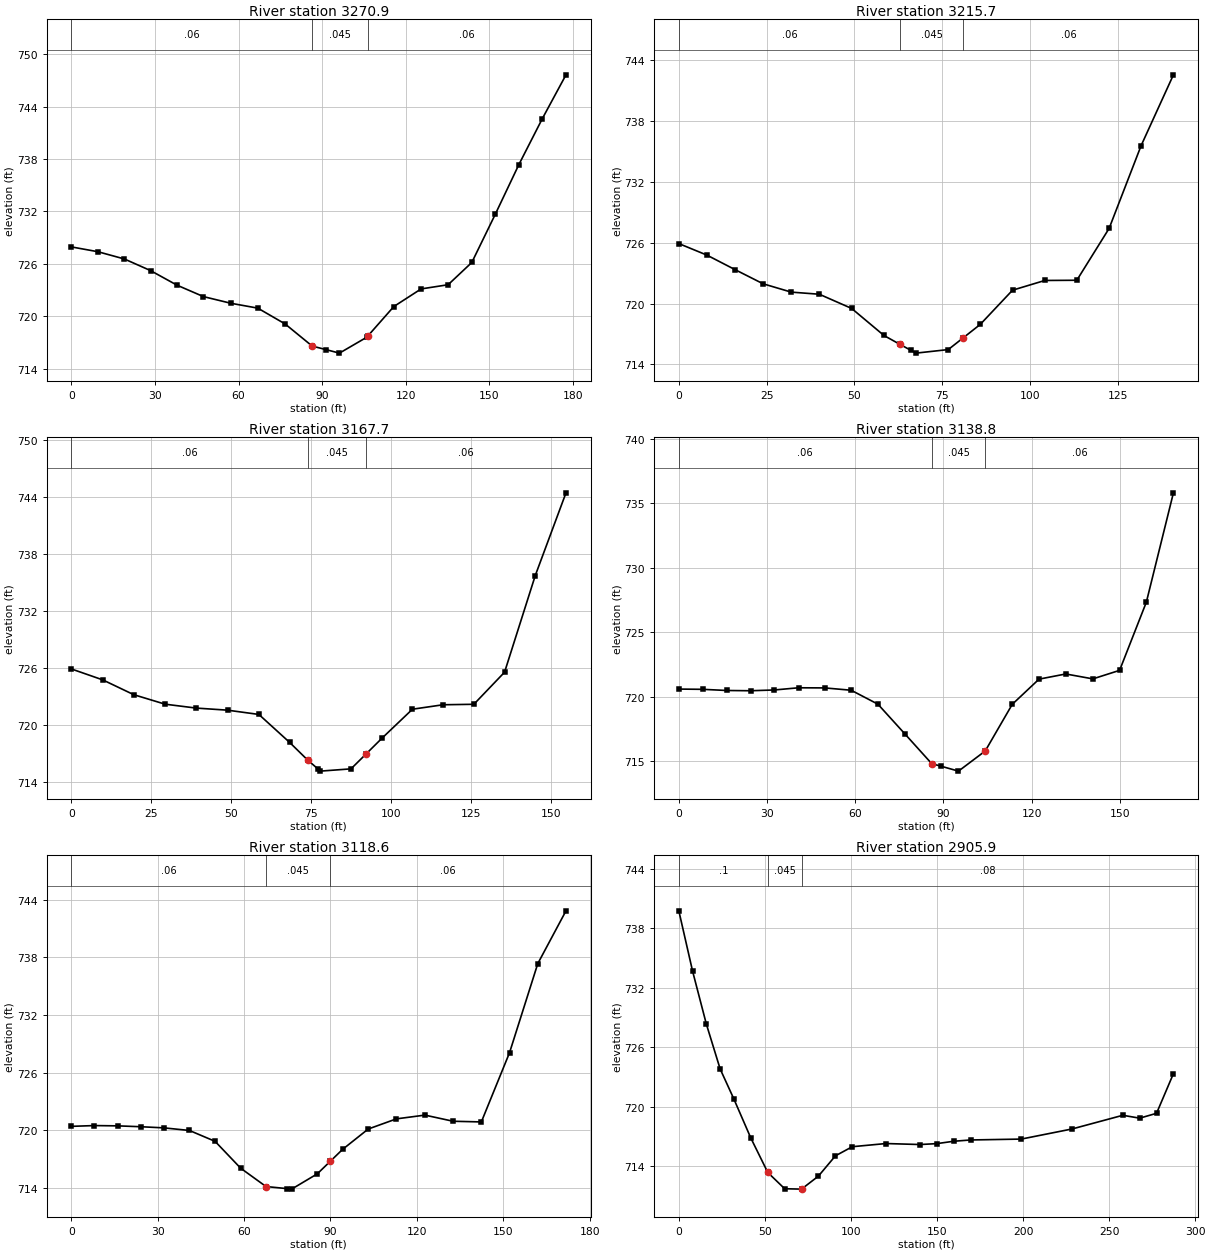
Type RM Length L Ch R = 1 ,3270.9  ,55,55.2,55.2
XS GIS Cut Line= 4
     1835422.499      507065.533     1835422.499      507112.929
     1835446.978      507197.304     1835453.749      507238.971
#Sta/Elev= 22
       0  727.94     9.5  727.39      19  726.56    28.4  725.23    37.9  723.56
    47.4  722.25    57.2  721.49    66.9  720.93    76.7  719.12    86.4  716.59
    91.5  716.17    96.2  715.78     106   717.6   106.5  717.78   115.7  721.11
   125.5  723.13   135.2  723.61   143.7  726.16   152.1  731.66   160.6  737.37
     169  742.62   177.5  747.64
#Mann= 3 , 0 , 0
       0     .06       0    86.4    .045       0   106.5     .06       0
Bank Sta=86.4,106.5
XS Rating Curve= 0 ,0
Exp/Cntr=0.3,0.1

Type RM Length L Ch R = 1 ,3215.7  ,49.4,48,46.7
XS GIS Cut Line= 3
     1835365.207      507104.075     1835374.062      507143.137
     1835401.666      507240.012
#Sta/Elev= 20
       0  725.93       8  724.79      16  723.36      24  721.96      32  721.14
      40  720.93    49.2  719.53    58.4  716.86   62.92  715.99      66  715.41
    67.5  715.12    76.7  715.47      81  716.64    85.8  717.95      95  721.33
   104.2  722.29   113.3  722.31   122.5  727.43   131.6  735.59   140.8  742.58
#Mann= 3 , 0 , 0
       0     .06       0   62.92    .045       0      81     .06       0
Bank Sta=62.92,81
XS Rating Curve= 0 ,0
Exp/Cntr=0.3,0.1

Type RM Length L Ch R = 1 ,3167.7  ,28,28.9,29.7
XS GIS Cut Line= 3
     1835333.437      507104.596     1835328.228      507162.929
     1835359.999      507253.554
#Sta/Elev= 20
       0  725.93     9.8  724.78    19.5  723.22    29.3  722.22      39  721.81
    48.8  721.59    58.6  721.14    68.2   718.2   73.84  716.34      77  715.42
    77.8  715.17    87.4  715.41      92  716.94      97  718.61   106.6  721.69
   116.2  722.16   125.8  722.21   135.4  725.59     145  735.77   154.6  744.48
#Mann= 3 , 0 , 0
       0     .06       0   73.84    .045       0      92     .06       0
Bank Sta=73.84,92
XS Rating Curve= 0 ,0
Exp/Cntr=0.3,0.1

Type RM Length L Ch R = 1 ,3138.8  ,19.3,20.2,20.7
XS GIS Cut Line= 4
     1835283.957      507105.811     1835295.242      507144.873
     1835299.062      507162.408     1835331.353      507267.096
#Sta/Elev= 21
       0   720.6     8.1  720.58    16.3  720.49    24.4  720.47    32.5  720.53
    40.7   720.7    49.6  720.69    58.6  720.51    67.7  719.43    76.9  717.12
      86  714.82    89.2  714.62    95.1  714.24   104.2   715.8   113.4  719.42
   122.5  721.37   131.6  721.77   140.8  721.39   149.9  722.05     159  727.34
   168.2  735.81
#Mann= 3 , 0 , 0
       0     .06       0      86    .045       0   104.2     .06       0
Bank Sta=86,104.2
XS Rating Curve= 0 ,0
Exp/Cntr=0.3,0.1

Type RM Length L Ch R = 1 ,3118.6  ,224.7,212.7,199.7
XS GIS Cut Line= 4
     1835277.013      507125.776     1835278.749      507157.894
     1835296.978      507226.471      1835327.36      507288.103
#Sta/Elev= 22
       0   720.4       8  720.48    16.1  720.45    24.1  720.36    32.2  720.24
      41  719.97    49.9  718.84    58.8  716.04    67.6  714.13      75  713.91
    76.5  713.86    85.4  715.45      90  716.78    94.2     718   103.1  720.12
   112.9  721.18   122.8  721.57   132.6  720.93   142.4  720.86   152.2  728.08
     162  737.35   171.8  742.85
#Mann= 3 , 0 , 0
       0     .06       0    67.6    .045       0      90     .06       0
Bank Sta=67.6,90
XS Rating Curve= 0 ,0
Exp/Cntr=0.3,0.1

Type RM Length L Ch R = 1 ,2905.9  ,278.6,268.8,259.7
XS GIS Cut Line= 3
     1835048.714      507148.346     1835075.624      507165.707
      1835260.52      507341.922
#Sta/Elev= 23
       0  739.76       8  733.67      16  728.33      24  723.81      32  720.77
    41.8  716.85    51.7  713.36    61.5  711.72    71.3  711.68    81.1  712.99
      91  715.04   100.8  715.96   120.4  716.28   140.1  716.18   149.9  716.27
   159.7  716.51   169.6  716.64     199  716.73   228.5  717.75     258  719.13
   267.8  718.84   277.6  719.33   287.4  723.33
#Mann= 3 , 0 , 0
       0      .1       0    51.7    .045       0    71.3     .08       0
Bank Sta=51.7,71.3
XS Rating Curve= 0 ,0
Exp/Cntr=0.3,0.1

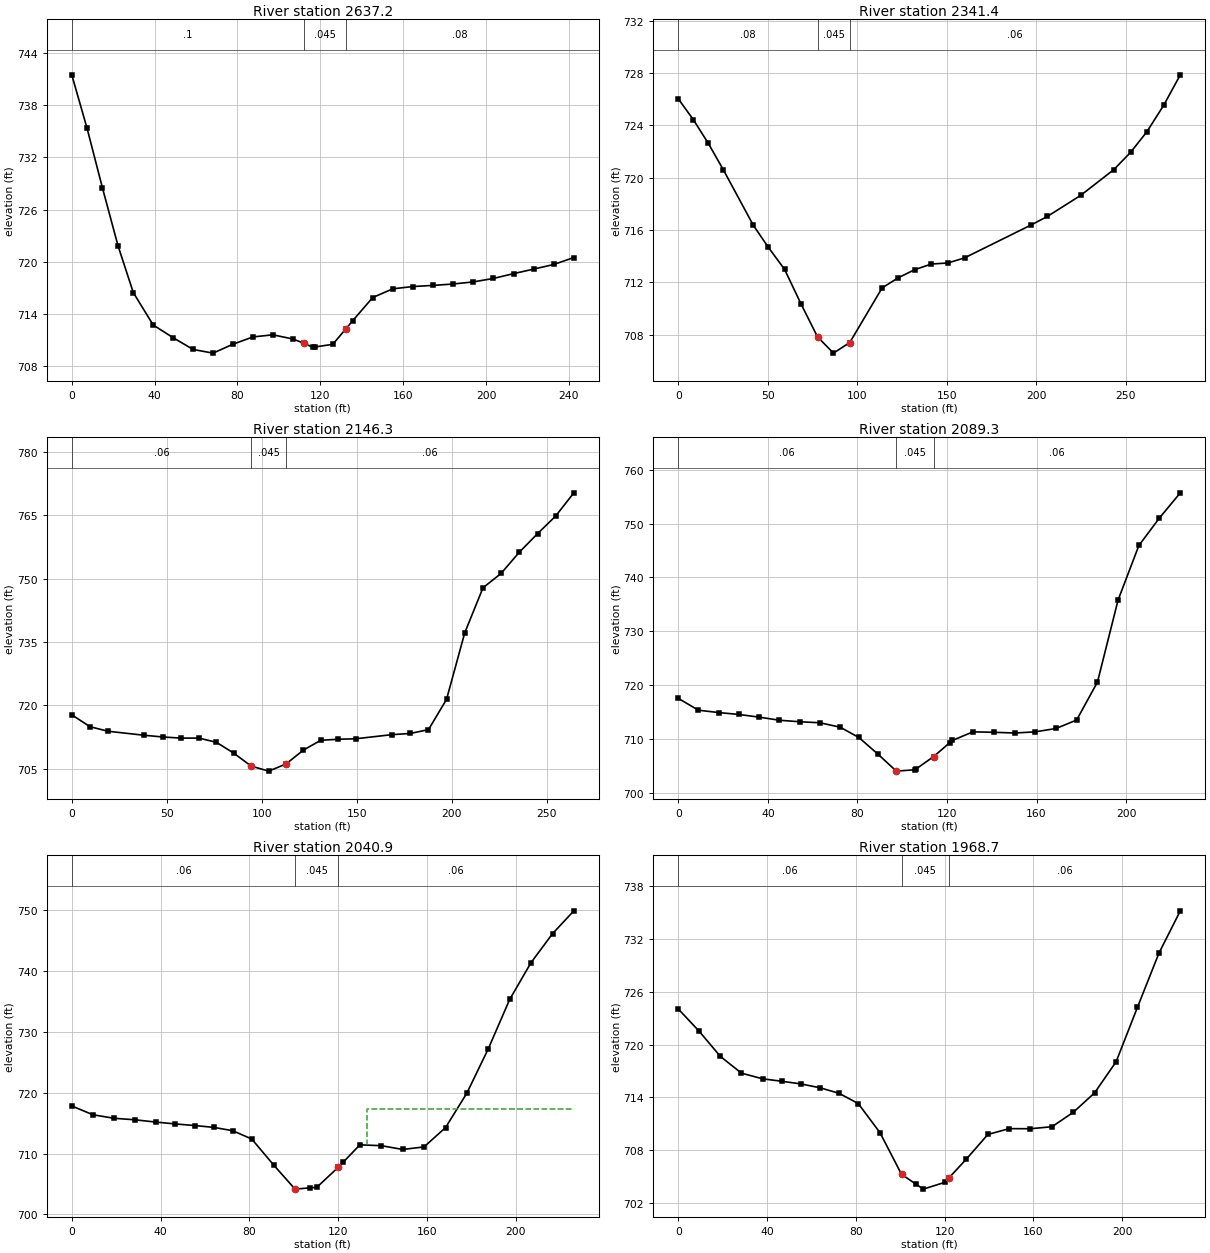
Type RM Length L Ch R = 1 ,2637.2  ,275.9,295.7,303.8
XS GIS Cut Line= 4
     1835022.673      507385.325     1835051.319      507393.137
     1835161.562      507427.859     1835246.631      507474.734
#Sta/Elev= 30
       0  741.46     7.4  735.31    14.8   728.5    22.3  721.87    29.7  716.48
    39.3  712.76      49  711.29    58.6  709.95    68.2  709.53    77.8  710.55
    87.5  711.39    97.1  711.63   106.8  711.15  112.05  710.66   116.4   710.2
   117.2  710.23     126  710.54   132.2  712.28   135.6  713.24   145.3  715.91
     155  716.91   164.7  717.17   174.4   717.3   184.1  717.46   193.8   717.7
   203.6   718.1   213.3  718.65     223  719.17   232.7   719.7   242.4   720.5
#Mann= 3 , 0 , 0
       0      .1       0  112.05    .045       0   132.2     .08       0
Bank Sta=112.05,132.2
XS Rating Curve= 0 ,0
Exp/Cntr=0.3,0.1

Type RM Length L Ch R = 1 ,2341.4  ,182.5,195.1,209.7
XS GIS Cut Line= 4
     1834968.853       507565.88     1834995.763      507608.415
      1835050.45      507669.179     1835178.055        507744.7
#Sta/Elev= 25
       0  726.02     8.4  724.43    16.8  722.61    25.2  720.59    41.9  716.36
    50.3  714.67    59.4  712.98    68.5  710.36    77.8  707.82    86.7  706.58
    95.8  707.39   113.9  711.57     123  712.35   132.1  712.96   141.4  713.39
   150.6  713.47   159.9  713.86     197  716.37   206.2  717.03   224.8  718.64
   243.3  720.61   252.6  721.92   261.8  723.51   271.1  725.52   280.4  727.85
#Mann= 3 , 0 , 0
       0     .08       0    77.8    .045       0    95.8     .06       0
Bank Sta=77.8,95.8
XS Rating Curve= 0 ,0
Exp/Cntr=0.3,0.1

Type RM Length L Ch R = 1 ,2146.3  ,53.9,57,59.8
XS GIS Cut Line= 4
     1834856.874      507608.415     1834859.478      507675.255
     1834857.742      507757.721      1834849.93      507872.304
#Sta/Elev= 27
       0  717.75     9.6  714.93    19.1  713.85    38.2   712.9    47.8   712.5
    57.3  712.23    66.9  712.23    76.1  711.24    85.2  708.68    94.4   705.6
   103.6  704.41   112.7  706.09   121.9  709.39     131  711.71   140.2  711.96
   149.4  712.07   168.5  713.05   178.1  713.33   187.7  714.23   197.2  721.39
   206.8  737.18   216.4  747.83   225.9  751.22   235.5  756.25   245.1  760.64
   254.6   764.8   264.2  770.31
#Mann= 3 , 0 , 0
       0     .06       0    94.4    .045       0   112.7     .06       0
Bank Sta=94.4,112.7
XS Rating Curve= 0 ,0
Exp/Cntr=0.3,0.1

Type RM Length L Ch R = 1 ,2089.3  ,47.5,48.4,49
XS GIS Cut Line= 4
     1834814.339      507610.151     1834808.263        507682.2
      1834800.45      507731.679     1834785.694      507832.373
#Sta/Elev= 28
       0  717.61       9  715.41    18.1  714.97    27.1  714.62    36.2  714.12
    45.2  713.55    54.2  713.27    63.3  713.08    72.3  712.26    80.6  710.37
      89  707.33    97.4  704.12   105.7  704.37   106.3  704.55     114   706.8
   121.3  709.41   122.4   709.8   131.6   711.4   140.9  711.32   150.2  711.18
   159.4   711.4   168.7  712.02   177.9  713.59   187.2  720.62   196.4  735.81
   205.7  745.93   214.9  751.04   224.2  755.69
#Mann= 3 , 0 , 0
       0     .06       0    97.4    .045       0     114     .06       0
Bank Sta=97.4,114
XS Rating Curve= 0 ,0
Exp/Cntr=0.3,0.1

Type RM Length L Ch R = 1 ,2040.9  ,72.2,72.2,72.2
XS GIS Cut Line= 5
     1834807.395      507611.887     1834785.694      507643.137
     1834761.388      507678.728     1834751.839      507726.471
     1834738.819      507821.957
#Sta/Elev= 27
       0  717.81     9.5  716.37      19  715.79    28.5  715.54      38  715.16
    46.7  714.86    55.3   714.6    63.9   714.3    72.5  713.75    81.1  712.38
    90.9  708.14   100.6  704.16   107.3  704.37   110.4  704.46   120.1  707.76
   122.3  708.59   129.8  711.43   139.5  711.29   149.1  710.67   158.7  711.09
   168.4  714.26     178  719.92   187.6  727.15   197.3   735.3   206.9  741.33
   216.6  746.09   226.2  749.84
#Mann= 3 , 0 , 0
       0     .06       0   100.6    .045       0   120.1     .06       0
#XS Ineff= 2 , 0
                          132.86          717.35
Permanent Ineff=
       F       F
Bank Sta=100.6,120.1
XS Rating Curve= 0 ,0
Exp/Cntr=0.3,0.1

Type RM Length L Ch R = 1 ,1968.7  ,52.5,48.4,44.8
XS GIS Cut Line= 5
      1834737.95       507592.79     1834716.249       507624.04
     1834691.944       507659.63     1834682.395      507707.373
     1834669.374      507802.859
#Sta/Elev= 27
       0  724.05     9.5  721.49      19  718.65    28.5  716.75      38  716.11
    46.7  715.83    55.3  715.53    63.9  715.09    72.5  714.46    81.1   713.3
    90.9  709.99   100.6  705.26   106.9  704.18   110.4  703.58   120.1  704.35
   121.9  704.84   129.8  706.99   139.5  709.79   149.1  710.45   158.7  710.44
   168.4  710.67     178  712.31   187.6  714.52   197.3  718.06   206.9  724.24
   216.6   730.4   226.2  735.19
#Mann= 3 , 0 , 0
       0     .06       0   100.6    .045       0   121.9     .06       0
Bank Sta=100.6,121.9
XS Rating Curve= 0 ,0
Exp/Cntr=0.3,0.1

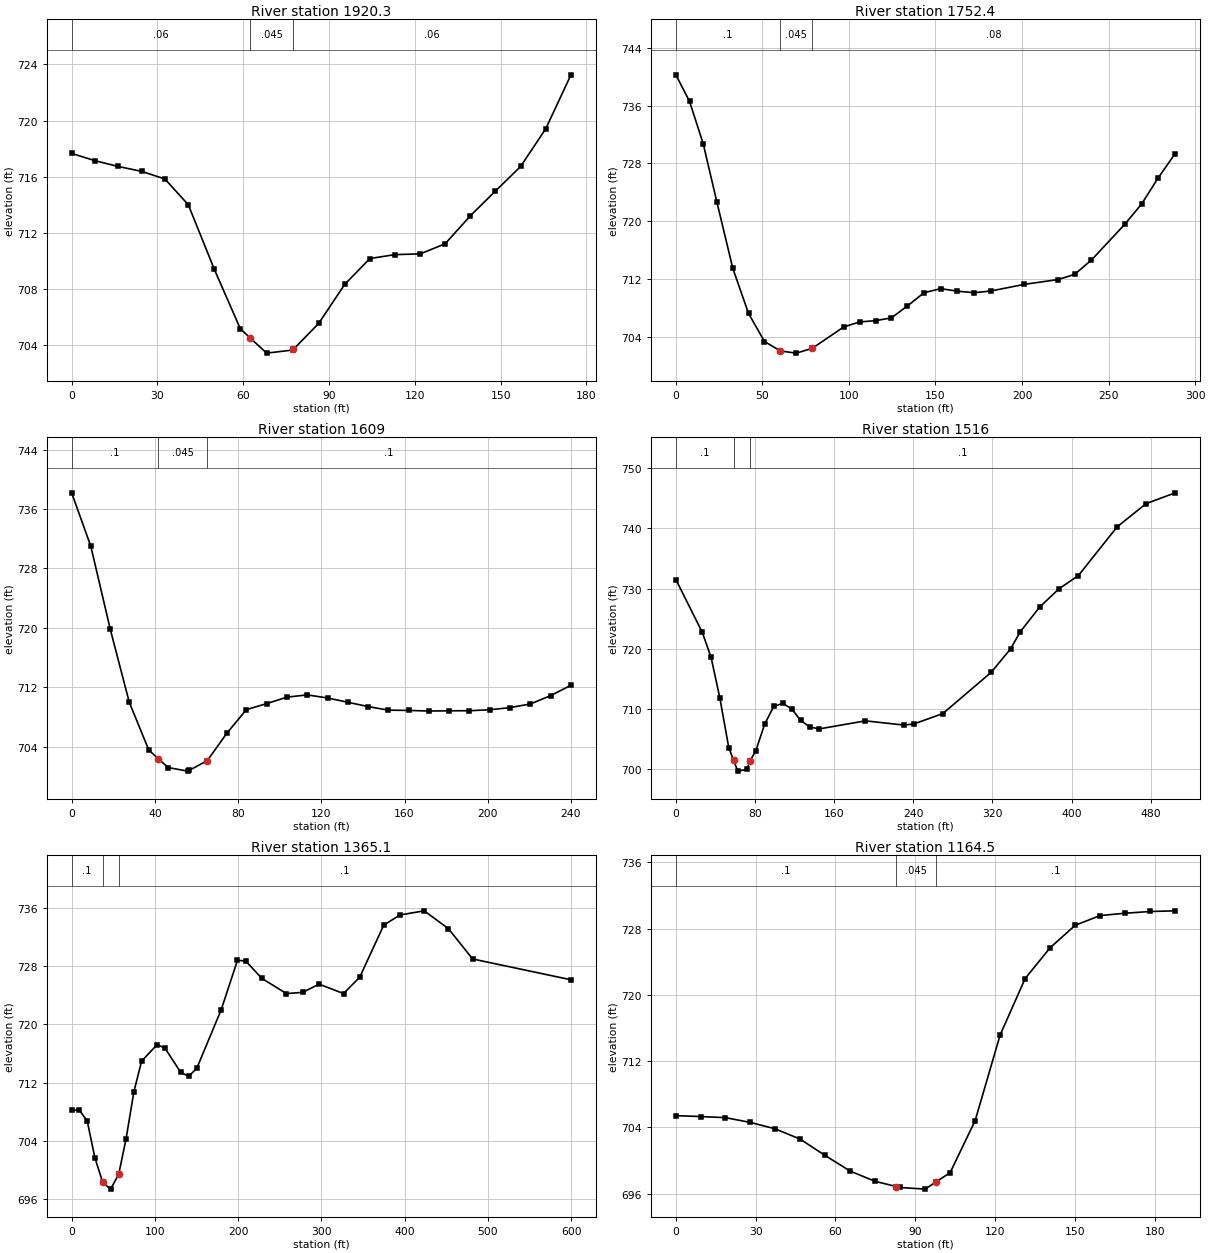
Type RM Length L Ch R = 1 ,1920.3  ,177.6,167.9,157
XS GIS Cut Line= 4
     1834638.124      507615.359     1834638.124      507656.158
     1834637.256      507710.846     1834641.596      507789.839
#Sta/Elev= 23
       0  717.66     8.2  717.14    16.3  716.73    24.5  716.38    32.6  715.84
    40.8     714    49.9   709.4      59  705.16    62.5   704.5    68.2  703.43
    77.3  703.65    77.5  703.69    86.4  705.55    95.5  708.33   104.3  710.17
   113.1  710.45   121.9   710.5   130.6  711.22   139.4  713.21   148.2  714.98
     157  716.73   165.8  719.42   174.6  723.26
#Mann= 3 , 0 , 0
       0     .06       0    62.5    .045       0    77.5     .06       0
Bank Sta=62.5,77.5
XS Rating Curve= 0 ,0
Exp/Cntr=0.3,0.1

Type RM Length L Ch R = 1 ,1752.4  ,149,143.4,138.8
XS GIS Cut Line= 4
     1834437.603      507610.151     1834447.152      507631.853
     1834491.423      507732.547     1834547.846      507876.644
#Sta/Elev= 28
       0  740.28     7.9   736.6    15.8  730.73    23.7  722.65    32.9  713.47
      42  707.22    51.2  703.34    60.4  702.03    69.5  701.73    78.7  702.38
      97  705.36   106.2  706.05   115.4  706.23   124.5  706.61   133.7  708.25
   143.4   710.1     153  710.66   162.7  710.31   172.4   710.1   182.1  710.34
   201.4  711.26   220.8  711.92   230.4  712.64   240.1  714.62   259.4  719.58
   269.1  722.39   278.8  726.05   288.5  729.37
#Mann= 3 , 0 , 0
       0      .1       0    60.4    .045       0    78.7     .08       0
Bank Sta=60.4,78.7
XS Rating Curve= 0 ,0
Exp/Cntr=0.3,0.1

Type RM Length L Ch R = 1 ,1609    ,93.7,93,91.1
XS GIS Cut Line= 4
     1834320.416      507709.978     1834335.173      507733.415
     1834369.895      507777.686     1834458.437      507906.158
#Sta/Elev= 28
       0  738.17     9.2     731    18.5  719.89    27.7  709.98    37.1  703.54
    41.6   702.4    46.4  701.19    55.8  700.71    56.6  700.83    65.2  702.12
    74.6  705.81      84  708.99    93.7  709.79   103.5  710.67   113.2  710.97
     123  710.56   132.7  709.98   142.5   709.4   152.2  708.92     162  708.88
   171.7   708.8   181.5  708.83   191.2  708.84     201  708.97   210.7  709.26
   220.5  709.75   230.2  710.87     240  712.27
#Mann= 3 , 0 , 0
       0      .1       0    41.6    .045       0    65.2      .1       0
Bank Sta=41.6,65.2
XS Rating Curve= 0 ,0
Exp/Cntr=0.3,0.1

Type RM Length L Ch R = 1 ,1516    ,126.1,150.8,176.3
XS GIS Cut Line= 5
     1834261.388      507758.589     1834270.937      507801.991
     1834326.492      507861.887     1834387.256      507886.193
     1834562.603      508145.741
#Sta/Elev= 30
       0  731.51    26.7  722.74    35.6  718.59    44.4   711.9    53.5   703.6
    58.4  701.51    62.6  699.72    71.7     700   74.93   701.4    80.8   703.1
    89.8  707.52    98.9  710.45     108  710.96   117.1  710.05   126.1  708.13
   135.5  707.04   144.8  706.72   191.6  708.06   230.7  707.36   240.5  707.54
   269.9  709.27   318.8  716.11   338.4  720.01   348.2  722.84   367.8  726.94
   387.4  729.98   406.9  732.16   446.1  740.24   475.4   744.1   504.8  745.89
#Mann= 3 , 0 , 0
       0      .1       0    58.4    .045       0   74.93      .1       0
Bank Sta=58.4,74.93
XS Rating Curve= 0 ,0
Exp/Cntr=0.3,0.1

Type RM Length L Ch R = 1 ,1365.1  ,191.3,200.6,210
XS GIS Cut Line= 6
     1834160.694      507796.783     1834112.082      507918.311
     1834143.332      507979.075     1834257.916       508034.63
      1834358.61      508152.686      1834412.43      508257.721
#Sta/Elev= 30
       0  708.22     9.4  708.21    18.7  706.75      28  701.67    37.4  698.31
    46.8   697.4    56.5  699.42    65.4   704.3    74.8  710.76    84.1  714.96
   102.8  717.22   112.2  716.71   130.9  713.43   140.6  712.85   150.4  713.98
   179.7     722   199.2  728.76     209  728.68   228.6  726.28     258  724.21
   277.6  724.37   297.2   725.5   326.6  724.21     346  726.44     375   733.6
   394.4  734.98   423.5  735.55   452.6  733.11   481.7  728.95   599.8   726.1
#Mann= 3 , 0 , 0
       0      .1       0    37.4    .045       0    56.5      .1       0
Bank Sta=37.4,56.5
XS Rating Curve= 0 ,0
Exp/Cntr=0.3,0.1

Type RM Length L Ch R = 1 ,1164.5  ,222.1,218.5,213.8
XS GIS Cut Line= 3
      1834041.77      507688.276     1834008.784      507705.637
     1833901.145      507810.672
#Sta/Elev= 23
       0  705.43     9.3  705.32    18.6  705.19      28  704.61    37.3  703.84
    46.7   702.6    56.1  700.62    65.5  698.74    74.9   697.5    82.9  696.87
    84.3  696.76    93.7  696.56    97.9  697.45   103.1  698.55   112.5  704.83
   121.9  715.17   131.3  721.98   140.7   725.7   150.1   728.4   159.5  729.58
   168.9  729.86   178.3  730.07   187.7  730.15
#Mann= 3 , 0 , 0
       0      .1       0    82.9    .045       0    97.9      .1       0
Bank Sta=82.9,97.9
XS Rating Curve= 0 ,0
Exp/Cntr=0.3,0.1