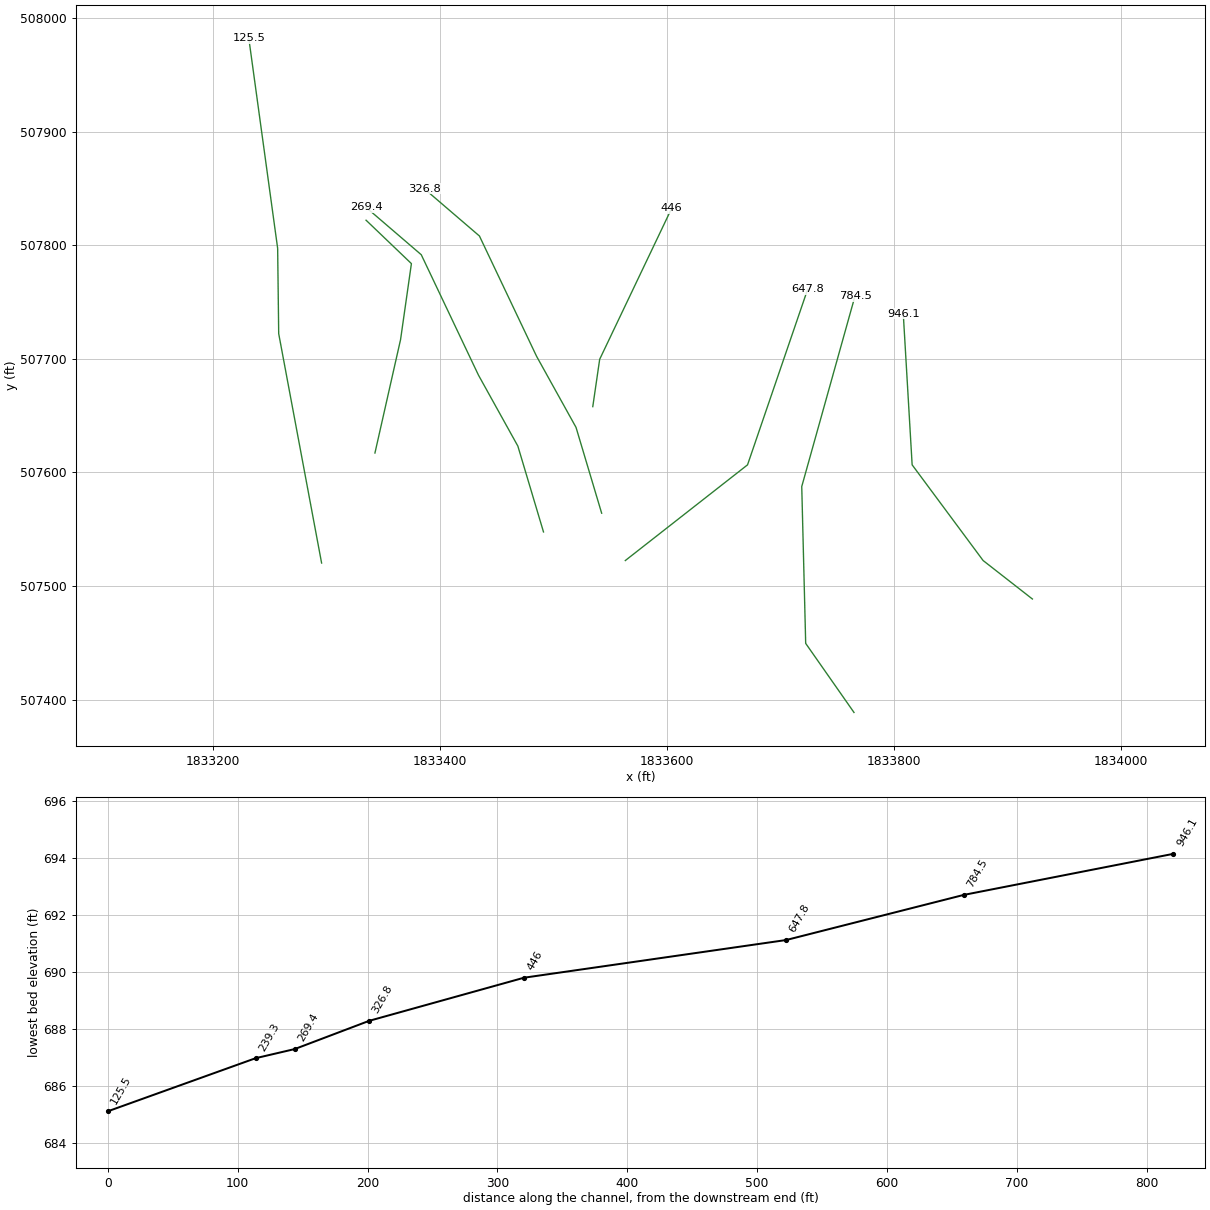
HEC-RAS study INDIANSCK.prj: INDIANSCK

--- INDIANSCK.g01 (geometry) --- (continued)

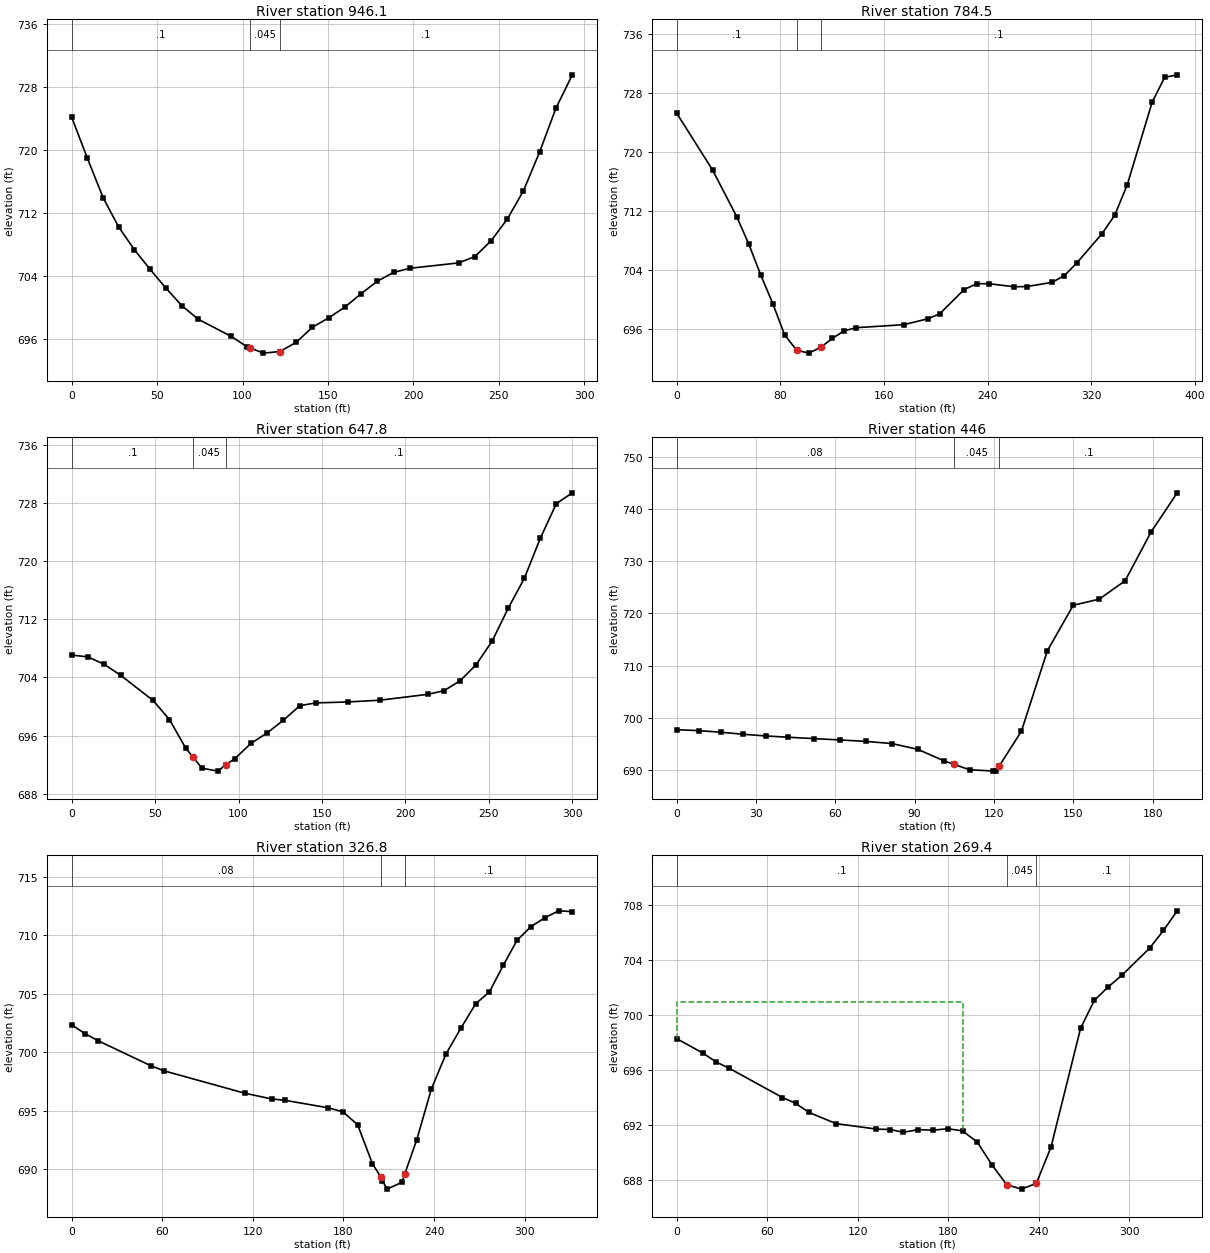
Type RM Length L Ch R = 1 ,946.1   ,175.1,161.5,147.9
XS GIS Cut Line= 4
     1833921.978      507488.623     1833878.575      507522.478
     1833816.075      507606.679     1833808.263      507739.491
#Sta/Elev= 30
       0  724.16     9.2  718.93    18.4  713.92    27.5  710.19    36.7   707.3
    45.9   704.8      55  702.45    64.6  700.15    74.1  698.45    93.2  696.29
   102.7  694.94   104.6  694.78   112.2  694.14   121.8  694.34   131.3   695.5
   140.8  697.42   150.4  698.63   159.9     700   169.4  701.71   178.9   703.3
   188.4  704.41   197.9  704.94   226.4  705.62   235.9  706.42   245.4  708.42
   254.9  711.19   264.4   714.8   273.9  719.76   283.4  725.31     293  729.56
#Mann= 3 , 0 , 0
       0      .1       0   104.6    .045       0   121.8      .1       0
Bank Sta=104.6,121.8
XS Rating Curve= 0 ,0
Exp/Cntr=0.3,0.1

Type RM Length L Ch R = 1 ,784.5   ,157.5,136.7,115.2
XS GIS Cut Line= 4
      1833764.86      507388.797     1833722.325      507449.561
     1833718.853      507587.582     1833765.728      507755.116
#Sta/Elev= 30
       0  725.27    27.8  717.53    46.4  711.21    55.6  707.54    64.9  703.31
    74.2  699.43    83.4  695.16    92.6   693.1   101.8   692.7   111.2  693.47
   120.2  694.71   129.4  695.73   138.6  696.15   175.4  696.56   193.8  697.36
     203  698.03   221.9  701.33   231.6  702.12   241.2  702.11   260.6   701.7
   270.2  701.73   289.6   702.3   299.2  703.22   308.9  704.96   328.2   708.9
   337.9  711.38   347.6  715.49   366.9  726.75   376.5   730.1   386.2  730.45
#Mann= 3 , 0 , 0
       0      .1       0    92.6    .045       0   111.2      .1       0
Bank Sta=92.6,111.2
XS Rating Curve= 0 ,0
Exp/Cntr=0.3,0.1

Type RM Length L Ch R = 1 ,647.8   ,189.4,201.8,212.7
XS GIS Cut Line= 3
     1833563.471      507522.478      1833671.11      507606.679
     1833724.062      507761.193
#Sta/Elev= 29
       0  707.08     9.8  706.82    19.5   705.8    29.3   704.3    48.8  700.83
    58.6   698.2    68.3  694.29    72.7  693.05    78.1  691.52    87.7  691.12
   92.21  691.99    97.6   692.8   107.4  694.93   117.1  696.37   126.9  698.12
   136.7  700.12   146.3   700.5   165.5  700.63   184.7  700.87   213.5  701.68
   223.1  702.18   232.7  703.53   242.4  705.76     252  709.02   261.6  713.52
   271.2  717.61   280.8  723.12   290.4  727.89     300  729.38
#Mann= 3 , 0 , 0
       0      .1       0    72.7    .045       0   92.21      .1       0
Bank Sta=72.7,92.21
XS Rating Curve= 0 ,0
Exp/Cntr=0.3,0.1

Type RM Length L Ch R = 1 ,446     ,99,119.2,139.2
XS GIS Cut Line= 3
     1833534.825      507657.894     1833540.902      507699.561
      1833604.27      507832.373
#Sta/Elev= 24
       0  697.72     8.4  697.55    16.8  697.24    25.3  696.85    33.7  696.53
    42.1  696.29    51.9  696.02    61.7  695.77    71.5  695.49    81.4  695.08
    91.2  693.97     101  691.79   104.8  691.12   110.8  690.06   119.8  689.82
   120.6   689.8  122.05   690.8   130.4  697.45   140.2  712.82     150  721.54
   159.8   722.7   169.6  726.22   179.4  735.54   189.3  743.05
#Mann= 3 , 0 , 0
       0     .08       0   104.8    .045       0  122.05      .1       0
Bank Sta=104.8,122.05
XS Rating Curve= 0 ,0
Exp/Cntr=0.3,0.1

Type RM Length L Ch R = 1 ,326.8   ,57.1,57.4,57.1
XS GIS Cut Line= 5
     1833542.638      507564.144     1833520.069      507639.665
     1833485.346      507702.165     1833434.999      507808.068
     1833386.388      507849.734
#Sta/Elev= 29
       0  702.35     8.8   701.6    17.5  700.99    52.6  698.84    61.3  698.41
   114.6   696.5   132.4  696.01   141.4  695.89   169.9  695.25   179.6  694.91
   189.4   693.8   199.2  690.46  204.61  689.36   205.7  689.02     209  688.29
   218.7  688.88   220.7  689.62   228.5  692.49   238.3  696.89     248  699.88
   257.8  702.07   267.6  704.16   276.7  705.17   285.9  707.46     295  709.59
   304.2  710.76   313.3  711.51   322.5  712.11   331.6  712.04
#Mann= 3 , 0 , 0
       0     .08       0  204.61    .045       0   220.7      .1       0
Bank Sta=204.61,220.7
XS Rating Curve= 0 ,0
Exp/Cntr=0.3,0.1

Type RM Length L Ch R = 1 ,269.4   ,43.7,30.1,16.5
XS GIS Cut Line= 5
     1833491.423      507547.651     1833468.853      507623.172
     1833434.131      507685.672     1833383.784      507791.575
     1833335.173      507833.241
#Sta/Elev= 28
       0  698.26    17.5   697.2    26.3  696.55      35  696.09    70.1  693.97
    78.8  693.55    87.8  692.88   105.6  692.07   132.4  691.67   141.4  691.64
   150.3  691.44   160.1  691.63   169.9  691.59   179.6   691.7   189.4  691.54
   199.2  690.72     209  689.05   218.7  687.62   228.5   687.3   238.3  687.72
     248  690.36   267.6  699.01   276.7  701.04   285.9  702.02     295  702.87
   313.3  704.84   322.5  706.13   331.6  707.56
#Mann= 3 , 0 , 0
       0      .1       0   218.7    .045       0   238.3      .1       0
#XS Ineff= 2 , 0
          189.54  700.91
Permanent Ineff=
       F       F
Bank Sta=218.7,238.3
XS Rating Curve= 0 ,0
Exp/Cntr=0.3,0.1

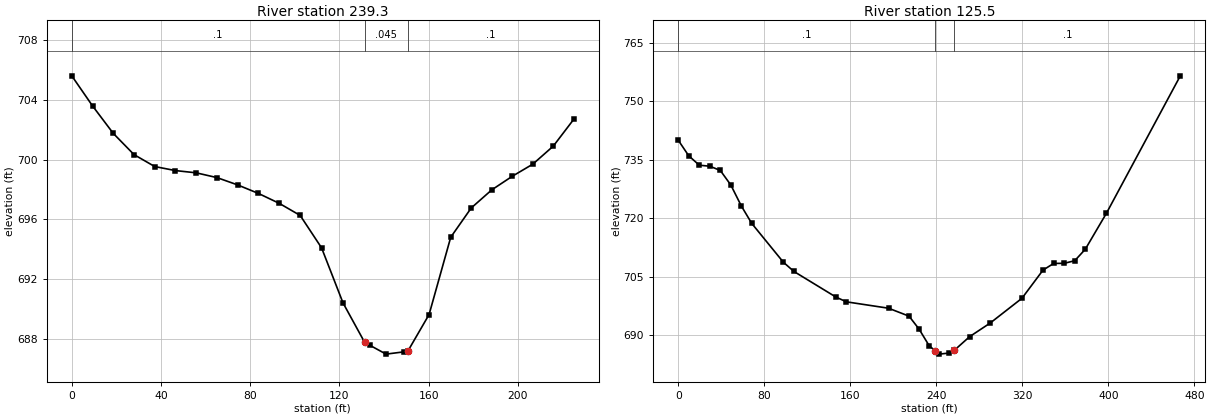
Type RM Length L Ch R = 1 ,239.3   ,110.3,113.8,117.2
XS GIS Cut Line= 4
     1833342.985      507617.096     1833365.555      507716.922
     1833375.103      507783.762     1833335.173      507821.957
#Sta/Elev= 27
       0   705.6     9.3  703.59    18.6  701.75    27.9  700.33    37.2  699.53
    46.5  699.26    55.8  699.11    65.1  698.79    74.4   698.3    83.7  697.73
      93  697.07   102.4  696.26     112  694.09   121.6  690.41   131.3  687.77
   133.8  687.56   140.9  686.98   148.8  687.13   150.6  687.16   160.2  689.63
   169.9   694.8   179.1  696.76   188.3  697.97   197.5  698.88   206.7  699.69
   215.9   700.9   225.1   702.7
#Mann= 3 , 0 , 0
       0      .1       0   131.3    .045       0   150.6      .1       0
Bank Sta=131.3,150.6
XS Rating Curve= 0 ,0
Exp/Cntr=0.3,0.1

Type RM Length L Ch R = 1 ,125.5   ,109.5,125.5,141.6
XS GIS Cut Line= 4
     1833296.011      507520.286     1833258.232       507722.12
     1833257.311      507797.176     1833231.905      507982.042
#Sta/Elev= 30
       0  740.06     9.8  736.04    19.6  733.64    29.3  733.38    39.1   732.3
    48.9  728.56    58.7  723.16    68.4  718.68    97.8  708.72   107.6  706.35
   146.7  699.77   156.4  698.55   195.6  696.91   214.7  694.87   224.1  691.51
   233.5  687.23     239     686   242.9  685.12   252.2  685.41  256.86  686.12
     271   689.6   290.2  693.11   319.7  699.46   339.3   706.7   349.2  708.41
     359  708.44   368.8  709.11   378.6  712.05   398.3  721.31     467  756.59
#Mann= 3 , 0 , 0
       0      .1       0     239    .045       0  256.86      .1       0
Bank Sta=239,256.86
XS Rating Curve= 0 ,0
Exp/Cntr=0.3,0.1

Chan Stop Cuts=-1
Use User Specified Reach Order=0
Composite Channel Slope=5